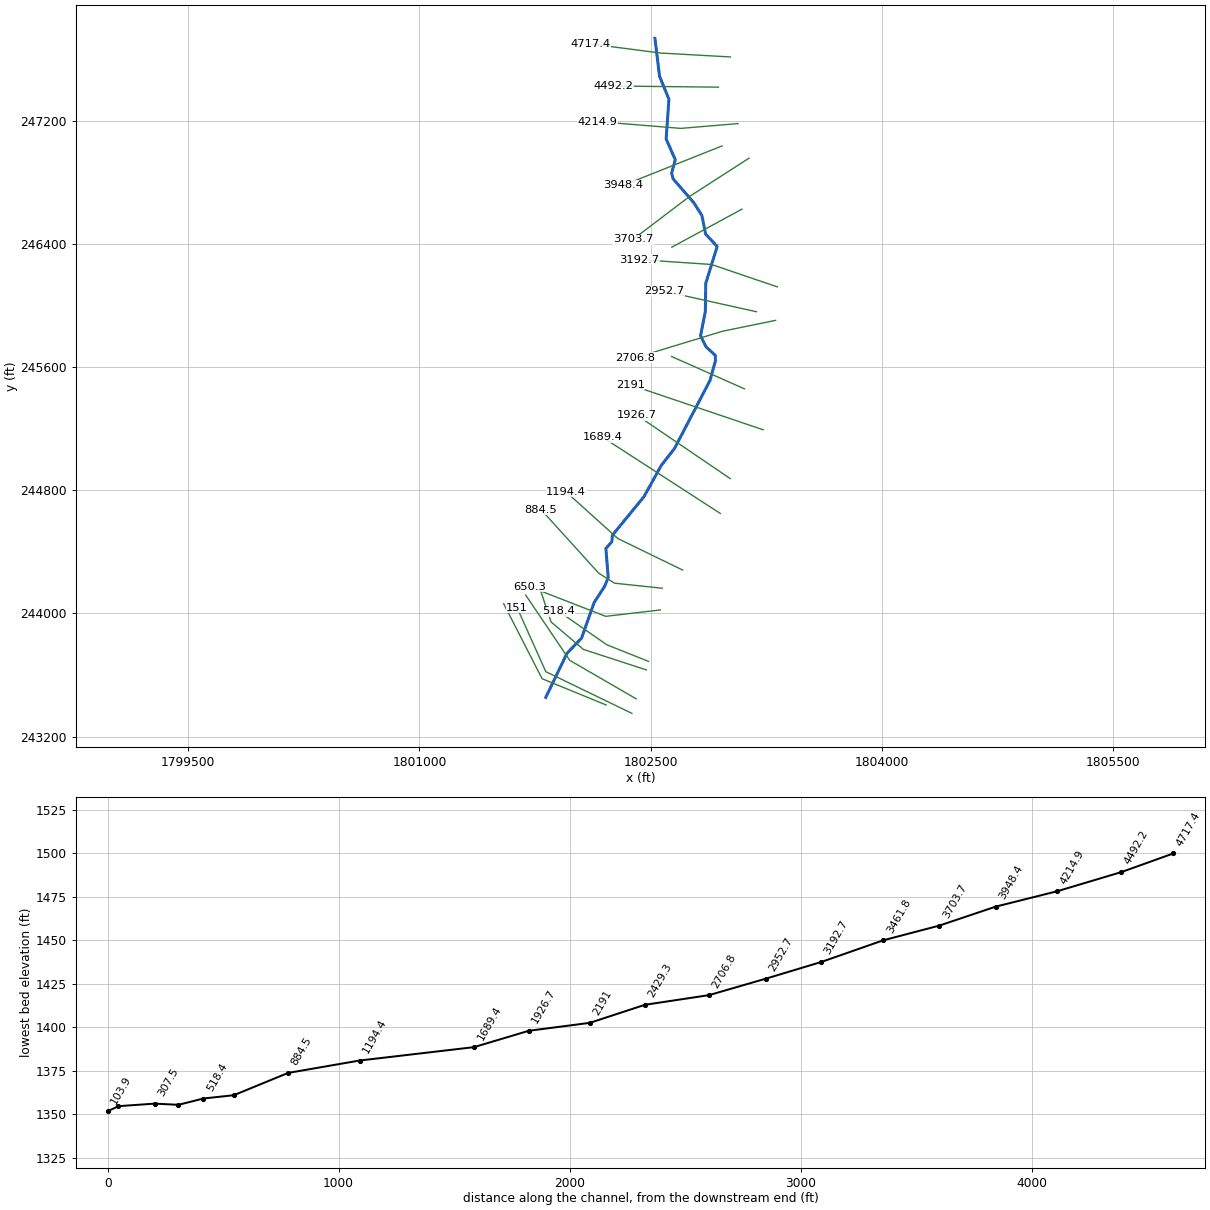
--- CabinBr.prj (project) ---

Proj Title=CabinBr
Current Plan=p01
Default Exp/Contr=0,0
English Units
Geom File=g01
Flow File=f01
Plan File=p01
BEGIN DESCRIPTION:
END DESCRIPTION:
DSS Export Rating Curves= 0
DSS Export Rating Curve Sorted= 0
DSS Export Volume Flow Curves= 0
DXF OffsetX= 0
DXF OffsetY= 0
DXF ScaleX= 0
DXF ScaleY= 0

--- CabinBr.p01 (plan) ---

Plan Title=Floodplain
Program Version=4.00
Geom File=g01
Flow File=f01
K Sum by GR=0
Std Step Tol=0.01
Critical Tol=0.01
Num of Std Step Trials=20
Max Error Tol=0.3
Flow Tol Ratio=0.001
Split Flow NTrial=30
Split Flow Tol=0.02
Split Flow Ratio=0.02
Log Output Level=0
Friction Slope Method=1
Unsteady Friction Slope Method=2
Unsteady Bridges Friction Slope Method=1
Global Log Level=0
CheckData=False
Run HTab=0
Run UNet=0
Run PostProcess=0
UNET Theta=0
UNET Theta Warmup=0
UNET ZTol=0
UNET ZSATol=0
UNET MxIter=0
UNET MaxInSteps=0
UNET DtIC=0
UNET DtMin=0
UNET MaxCRTS=0
UNET WFStab=0
UNET SFStab=0
UNET WFX=0
UNET SFX=0
UNET DSS MLevel=0
UNET DZMax Abort=0
UNET Convert EG Bridges=0
UNET Use Existing IB Tables=0
UNET Froude Limit=0
UNET Froude Power=0
Write IC File=0
Echo Input=False
Echo Output=False
Write Detailed=0

--- CabinBr.f01 (steady flow) ---

Flow Title=NFF Regression Equation
Program Version=4.00
Number of Profiles=1
Profile Names=P100yr
River Rch & RM=CabinBr,Main      ,4717.4
520.9686
River Rch & RM=CabinBr,Main      ,4214.9
543.7600
River Rch & RM=CabinBr,Main      ,3948.4
581.0443
River Rch & RM=CabinBr,Main      ,2952.7
618.7344
River Rch & RM=CabinBr,Main      ,2429.3
739.6049
River Rch & RM=CabinBr,Main      ,151
767.9598
Boundary for River Rch & Prof#=CabinBr,Main      ,1
Up Type=0
Dn Type=3
Dn Slope=0.019363

--- CabinBr.g01 (geometry) ---

Geom Title=USGS 10m DEM
Program Version=4.00

River Reach=CabinBr         ,Main
Reach XY= 30
     1802528.307      247739.666     1802558.387       247493.25
     1802619.237      247343.789     1802601.098      247085.308
     1802660.383      246950.599     1802636.677      246862.549
     1802646.837      246825.297     1802778.912      246672.902
     1802833.097      246588.238     1802856.803      246468.015
     1802932.134      246385.948     1802858.066      246146.615
     1802855.547      245964.721     1802824.308      245804.997
     1802860.586      245733.449     1802919.538      245679.032
     1802921.049      245643.761     1802885.275      245514.269
     1802655.303      245072.756     1802570.639      244964.386
      1802457.19      244759.499     1802252.303      244508.895
     1802248.916      244466.563     1802209.971      244422.537
      1802225.21        244234.5     1802202.543      244177.526
     1802133.514      244070.204     1802051.889      243838.931
     1801957.819      243741.338     1801820.142      243454.478

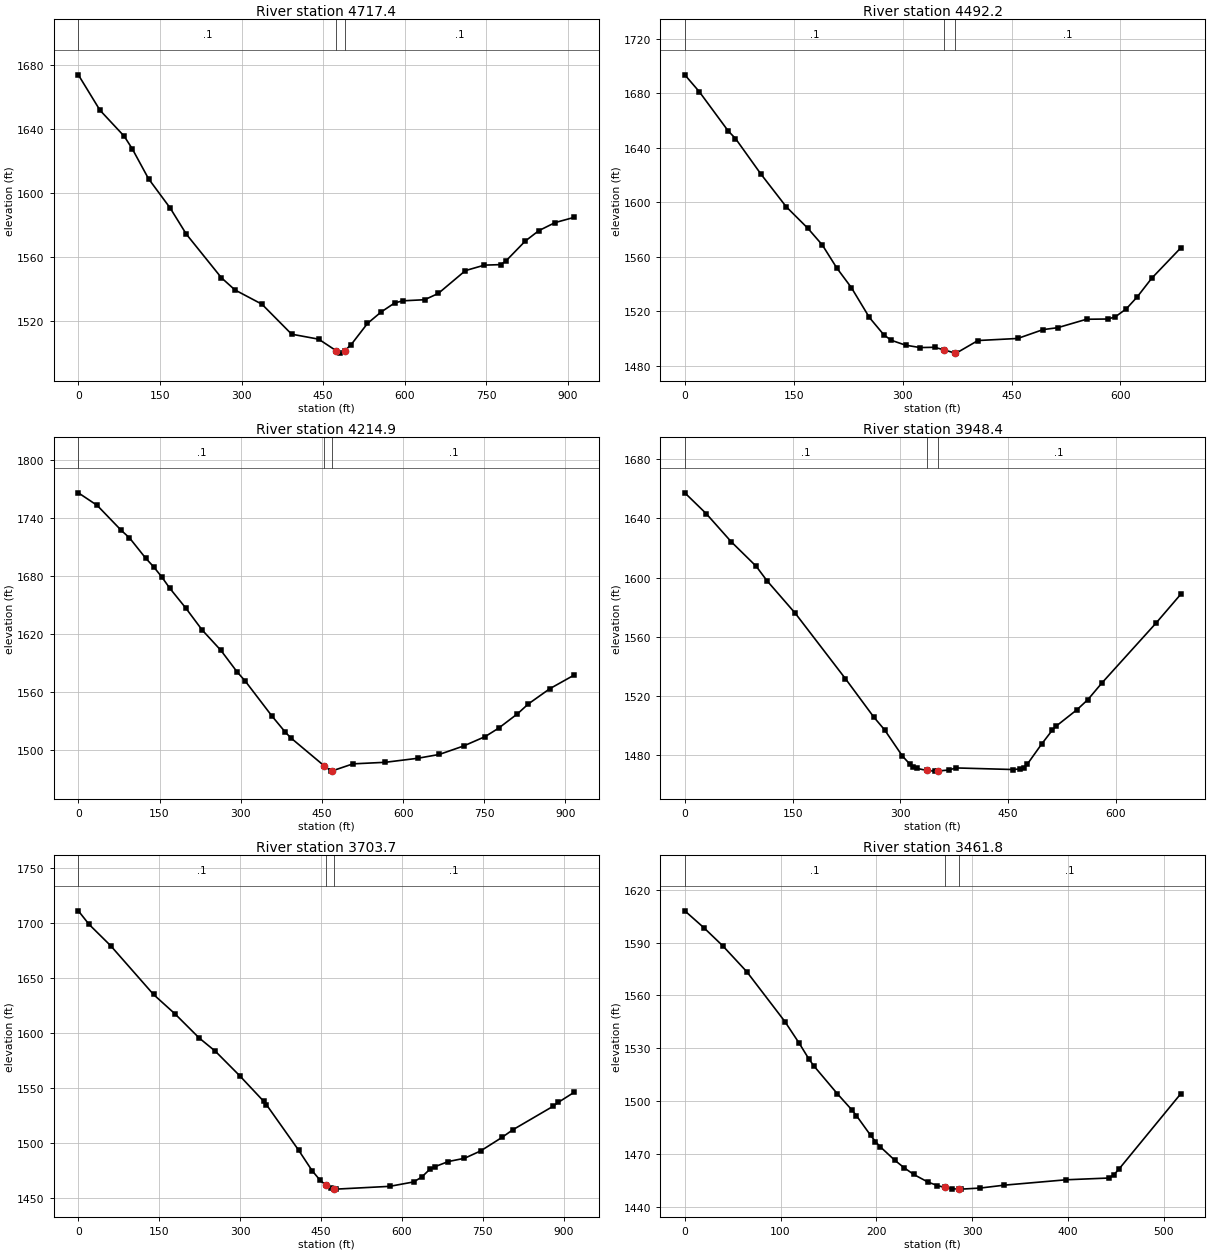
Type RM Length L Ch R = 1 ,4717.4  ,222.6,225.1,227.6
XS GIS Cut Line= 3
     1803018.307      247618.627     1802562.529      247644.248
     1802111.612      247703.063
#Sta/Elev= 30
       0 1673.97    39.7 1651.84    84.4 1635.51    99.2 1627.62     129 1608.95
   168.7 1590.66   198.5 1574.25     263 1546.96   287.8 1539.37   337.4 1530.44
     392 1511.67   441.6 1508.56   474.3 1501.24   481.5 1499.82   489.3 1501.24
   501.5 1505.19   531.4  1518.4   556.4 1525.54   581.4 1531.23   596.4 1532.55
   636.4 1533.24   661.4 1537.15   711.4 1551.47   746.3 1554.89   776.3  1555.2
   786.3 1557.66   821.3 1569.93   846.3 1576.47   876.2 1581.51   911.2 1584.77
#Mann= 3 , 0 , 0
       0      .1       0   474.3    .045       0   489.3      .1       0
Bank Sta=474.3,489.3
XS Rating Curve= 0 ,0
Exp/Cntr=0.3,0.1

Type RM Length L Ch R = 1 ,4492.2  ,279.2,277.3,275.4
XS GIS Cut Line= 2
      1802940.24      247422.285     1802257.448      247429.667
#Sta/Elev= 30
       0 1693.45    19.9  1681.1    59.8 1652.21    69.8 1646.68   104.7 1620.66
   139.6 1596.63   169.5 1580.74   189.4  1568.5   209.3 1551.64   229.3 1537.28
   254.2 1515.27   274.1 1502.55   284.1  1498.6     304 1494.95     324  1493.2
   343.9 1493.39   357.1 1491.49   372.1 1489.13   373.8 1489.11   403.7 1498.36
   458.5 1499.88   493.4 1506.39   513.4 1507.77   553.2 1513.98   583.2 1514.16
   593.1 1515.86   608.1 1521.68     623 1530.38     643  1544.1   682.8 1566.26
#Mann= 3 , 0 , 0
       0      .1       0   357.1    .045       0   372.1      .1       0
Bank Sta=357.1,372.1
XS Rating Curve= 0 ,0
Exp/Cntr=0.3,0.1

Type RM Length L Ch R = 1 ,4214.9  ,252,266.5,277.8
XS GIS Cut Line= 3
     1803068.084      247185.454     1802696.649       247154.09
     1802155.281      247198.565
#Sta/Elev= 30
       0 1766.22    34.8 1753.23    79.5 1727.23    94.4 1719.66   124.2 1698.71
   139.2 1689.58   154.1 1679.17     169 1667.42   198.8 1646.72   228.6 1624.32
   263.4 1603.13   293.2 1580.92   308.2 1571.45   357.8 1535.05   382.7 1518.24
   392.7 1512.48   454.5 1483.46   467.4 1478.12   469.5 1478.46   507.3 1485.64
   567.1 1487.26   626.9 1491.41   666.8 1495.38   711.6 1504.11   751.5 1513.84
   776.4 1522.58   811.3 1537.44   831.2  1547.6   871.1 1563.47     916 1577.55
#Mann= 3 , 0 , 0
       0      .1       0   454.5    .045       0   469.5      .1       0
Bank Sta=454.5,469.5
XS Rating Curve= 0 ,0
Exp/Cntr=0.3,0.1

Type RM Length L Ch R = 1 ,3948.4  ,244.1,244.7,249.3
XS GIS Cut Line= 2
     1802964.161      247040.154     1802323.335      246784.261
#Sta/Elev= 30
       0 1657.19    29.8 1643.14    64.5  1624.2    99.3 1607.63   114.2 1597.94
   153.9 1575.76   223.4 1531.77   263.1 1505.71     278 1497.17   302.8 1479.48
   312.8 1474.19   317.7 1472.22   322.7 1471.16   336.7 1469.73   347.5 1469.27
   351.7 1469.32   367.4 1470.02   377.3 1471.43   456.7 1470.35   466.6 1470.75
   471.6 1471.64   476.6 1473.93   496.4 1487.42   511.3 1496.86   516.3 1499.47
   546.1 1510.87     561  1517.6   580.8 1528.99   655.3 1568.97     690  1588.6
#Mann= 3 , 0 , 0
       0      .1       0   336.7    .045       0   351.7      .1       0
Bank Sta=336.7,351.7
XS Rating Curve= 0 ,0
Exp/Cntr=0.3,0.1

Type RM Length L Ch R = 1 ,3703.7  ,244.2,241.9,238.5
XS GIS Cut Line= 3
     1803138.706      246960.308     1802753.752      246711.954
     1802386.759      246433.052
#Sta/Elev= 30
       0 1710.92    19.9 1698.61    59.8 1679.33   139.4 1634.99   179.3 1617.34
   224.1 1595.47     254 1583.48   298.8 1561.42   343.6 1538.05   348.6 1535.04
   408.3 1493.73   433.2  1475.2   448.2 1466.38   459.3 1461.72     468 1459.51
   474.3 1458.65   477.9 1458.35   577.1 1460.88   621.7 1464.89   636.6 1469.34
   651.4 1476.28   661.3 1478.78   686.1 1483.42   715.8 1486.34   745.6 1492.98
   785.2 1505.24   805.1 1512.11   879.4 1533.35   889.3 1536.99   919.1 1546.23
#Mann= 3 , 0 , 0
       0      .1       0   459.3    .045       0   474.3      .1       0
Bank Sta=459.3,474.3
XS Rating Curve= 0 ,0
Exp/Cntr=0.3,0.1

Type RM Length L Ch R = 1 ,3461.8  ,288.1,269.2,255.9
XS GIS Cut Line= 2
     1803093.201      246628.976      1802638.28      246381.831
#Sta/Elev= 30
       0    1608    19.9 1598.41    39.8 1588.03    64.7 1573.43   104.5 1545.12
   119.5 1532.76   129.4    1524   134.4 1520.15   159.3 1504.09   174.2 1495.07
   179.2 1491.68   194.1 1480.43   199.1 1476.91   204.1 1473.99     219 1466.46
     229 1462.09     239 1458.28   253.9 1453.94   263.8 1451.97   271.6 1450.88
   278.8 1450.19   286.6 1449.95   288.7 1449.94   308.6 1450.56   333.5 1452.19
   398.2 1455.25     443 1456.25     448  1458.1     453 1461.11   517.7 1504.01
#Mann= 3 , 0 , 0
       0      .1       0   271.6    .045       0   286.6      .1       0
Bank Sta=271.6,286.6
XS Rating Curve= 0 ,0
Exp/Cntr=0.3,0.1

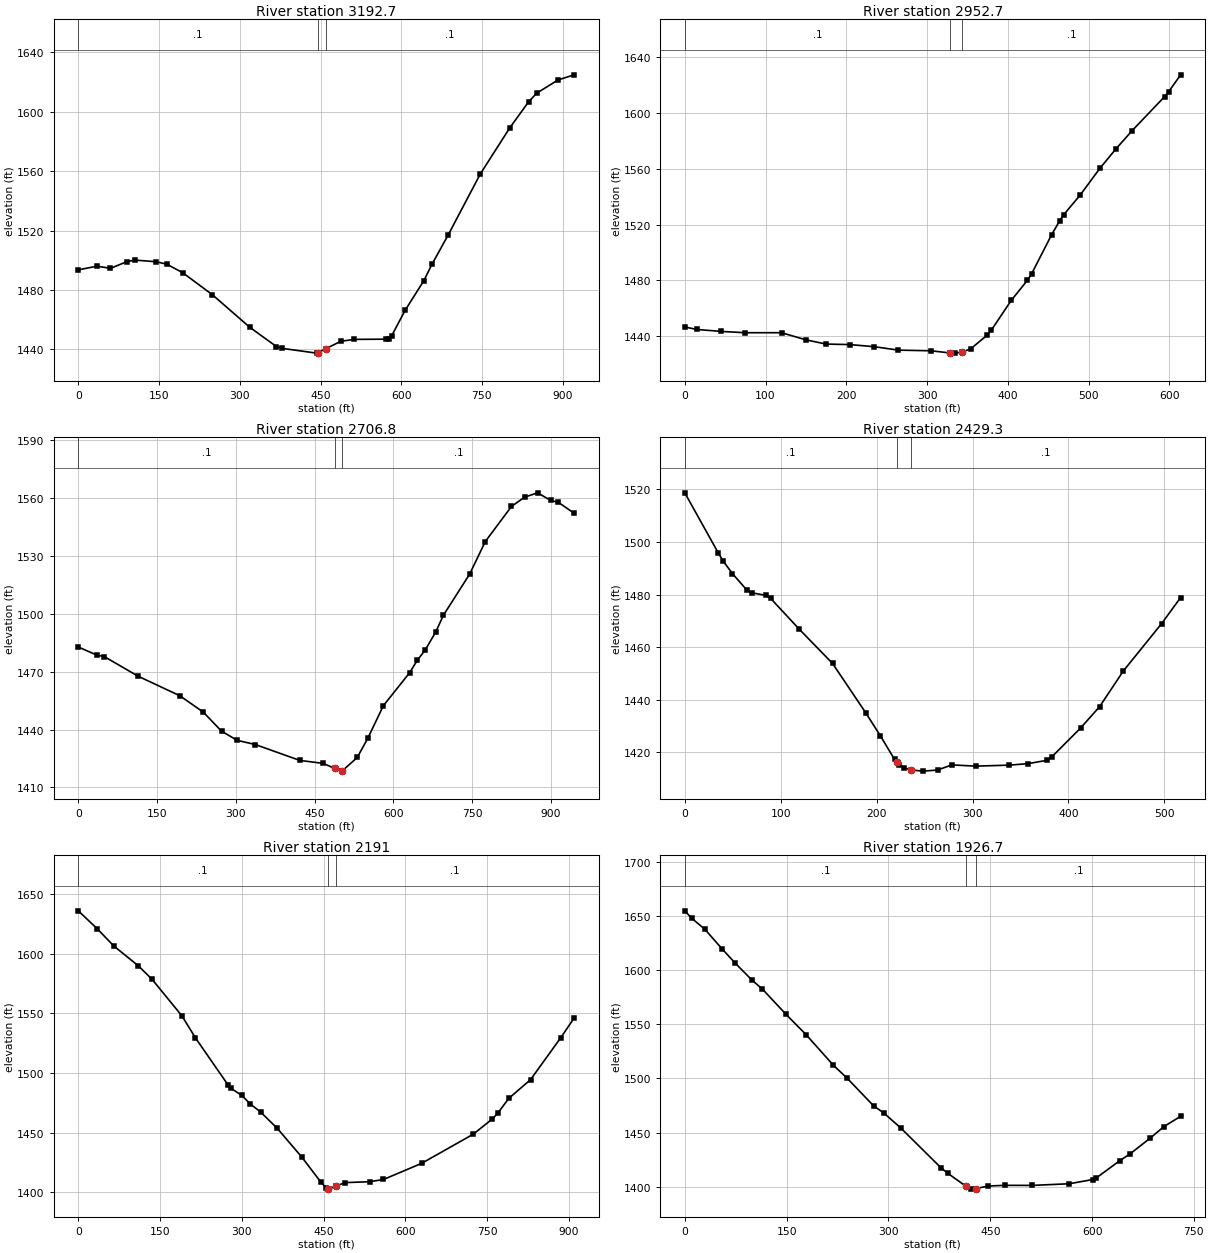
Type RM Length L Ch R = 1 ,3192.7  ,237.5,239.9,236.4
XS GIS Cut Line= 3
     1803323.053      246123.593     1802894.588      246269.431
      1802426.94      246300.713
#Sta/Elev= 30
       0 1493.52    34.8 1495.99    59.7 1494.53    89.5 1498.92   104.4  1500.1
   144.2    1499   164.1 1497.38     194 1491.57   248.7 1476.88   318.3 1454.92
     368  1441.9     378 1440.69   442.7 1437.45   445.1 1437.75   460.1 1440.46
   487.5  1445.4   512.4 1446.71   572.3 1446.84   577.3 1447.27   582.2 1449.12
   607.2 1466.26   642.1  1486.3     657  1497.2     687 1516.85   746.8 1558.01
   801.6 1589.09   836.5 1606.57   851.5 1612.42   891.4 1621.37   921.3 1624.82
#Mann= 3 , 0 , 0
       0      .1       0   445.1    .045       0   460.1      .1       0
Bank Sta=445.1,460.1
XS Rating Curve= 0 ,0
Exp/Cntr=0.3,0.1

Type RM Length L Ch R = 1 ,2952.7  ,233.9,245.9,257.9
XS GIS Cut Line= 2
     1803187.248      245961.904     1802587.977      246095.318
#Sta/Elev= 30
       0 1446.61      15 1444.83    44.9 1443.44    74.9 1442.49   119.8 1442.51
   149.7 1437.43   174.7 1434.38   204.6 1433.98   234.6 1432.48   264.5 1430.02
   304.5 1429.56   328.5 1427.99   334.4 1427.87   343.5 1428.57   354.4 1431.16
   374.4 1440.76   379.4 1444.24   404.3 1465.73   424.3 1480.16   429.3 1484.61
   454.2 1512.78   464.2 1522.75   469.2 1527.14   489.2 1540.93   514.1 1560.46
   534.1 1574.47     554 1587.43     594  1611.7     599 1615.16   613.9 1627.36
#Mann= 3 , 0 , 0
       0      .1       0   328.5    .045       0   343.5      .1       0
Bank Sta=328.5,343.5
XS Rating Curve= 0 ,0
Exp/Cntr=0.3,0.1

Type RM Length L Ch R = 1 ,2706.8  ,294,277.5,260.9
XS GIS Cut Line= 3
     1803311.347      245905.888     1802966.349      245835.051
     1802399.715      245661.996
#Sta/Elev= 30
       0 1482.76    34.7 1478.64    49.6 1477.77   114.1  1467.6   193.5 1457.49
   238.1    1449   272.8 1439.16   302.6 1434.38   337.3  1432.2   421.9 1423.98
   466.7 1422.43   488.1 1419.84   501.6 1418.42   503.1 1418.61   531.4  1425.5
   551.4 1435.38   581.2 1452.35     631 1469.35   645.9 1475.93   660.9 1481.21
   680.8 1490.47   695.7 1499.28   745.5 1520.53   775.4 1537.45   825.2 1555.62
   850.1 1560.44     875  1562.7   899.9 1558.77   914.8 1557.74   944.7  1552.1
#Mann= 3 , 0 , 0
       0      .1       0   488.1    .045       0   503.1      .1       0
Bank Sta=488.1,503.1
XS Rating Curve= 0 ,0
Exp/Cntr=0.3,0.1

Type RM Length L Ch R = 1 ,2429.3  ,235.7,238.3,240.9
XS GIS Cut Line= 2
     1803108.511      245461.053     1802636.093      245671.017
#Sta/Elev= 30
       0 1518.67    34.8 1495.89    39.8 1492.82    49.7 1487.95    64.6 1481.74
    69.6 1480.69    84.5 1479.67    89.5 1478.54   119.3 1466.84   154.1 1453.79
   188.9 1434.91   203.8 1426.37   218.7 1417.33   221.3  1416.2   223.7 1415.14
   228.7 1414.11   236.3 1413.28   248.6 1412.87   263.5 1413.28   278.4 1415.24
   303.2 1414.77     338 1415.14   357.9 1415.71   377.8    1417   382.8 1418.33
   412.6 1429.22   432.5 1437.37   457.3 1450.96   497.1 1468.92     517 1478.86
#Mann= 3 , 0 , 0
       0      .1       0   221.3    .045       0   236.3      .1       0
Bank Sta=221.3,236.3
XS Rating Curve= 0 ,0
Exp/Cntr=0.3,0.1

Type RM Length L Ch R = 1 ,2191    ,271,264.3,257.7
XS GIS Cut Line= 3
     1803230.376      245194.545      1802799.48      245340.675
     1802368.585      245486.806
#Sta/Elev= 30
       0    1636      35  1620.8      65 1606.55     110 1589.89     135 1578.72
     190 1547.94     215 1529.36     275 1489.77     280 1487.15     300 1481.13
     315 1474.23     335 1466.98     365 1453.56     410 1429.46     445 1408.46
     455 1403.46   457.6 1402.97     460 1402.51   472.6 1405.14     490 1407.98
     535 1408.74     560  1410.6     630 1424.12     725 1448.64     760 1461.44
     770 1466.38     790 1478.61     830 1494.38     885 1529.28     910 1546.11
#Mann= 3 , 0 , 0
       0      .1       0   457.6    .045       0   472.6      .1       0
Bank Sta=457.6,472.6
XS Rating Curve= 0 ,0
Exp/Cntr=0.3,0.1

Type RM Length L Ch R = 1 ,1926.7  ,236.6,237.3,238
XS GIS Cut Line= 2
     1803016.652      244877.092     1802413.007      245288.271
#Sta/Elev= 30
       0 1654.56     9.9 1647.86    29.8  1637.4    54.6  1619.7    74.5 1606.18
    99.4 1590.43   114.3 1582.41   149.1 1559.12   178.9  1540.2   218.6 1512.35
   238.5 1500.63   278.2 1474.68   293.2 1468.13     318 1454.41   377.6 1417.51
   387.6 1412.48   413.9 1400.69   422.3 1397.95   428.9 1398.48   447.2 1400.84
     472 1401.44   511.8 1401.38   566.4 1402.91   601.2 1406.82   606.2 1408.27
     641 1424.29   655.8 1430.37   685.7 1445.03   705.5 1455.49   730.4 1465.12
#Mann= 3 , 0 , 0
       0      .1       0   413.9    .045       0   428.9      .1       0
Bank Sta=413.9,428.9
XS Rating Curve= 0 ,0
Exp/Cntr=0.3,0.1

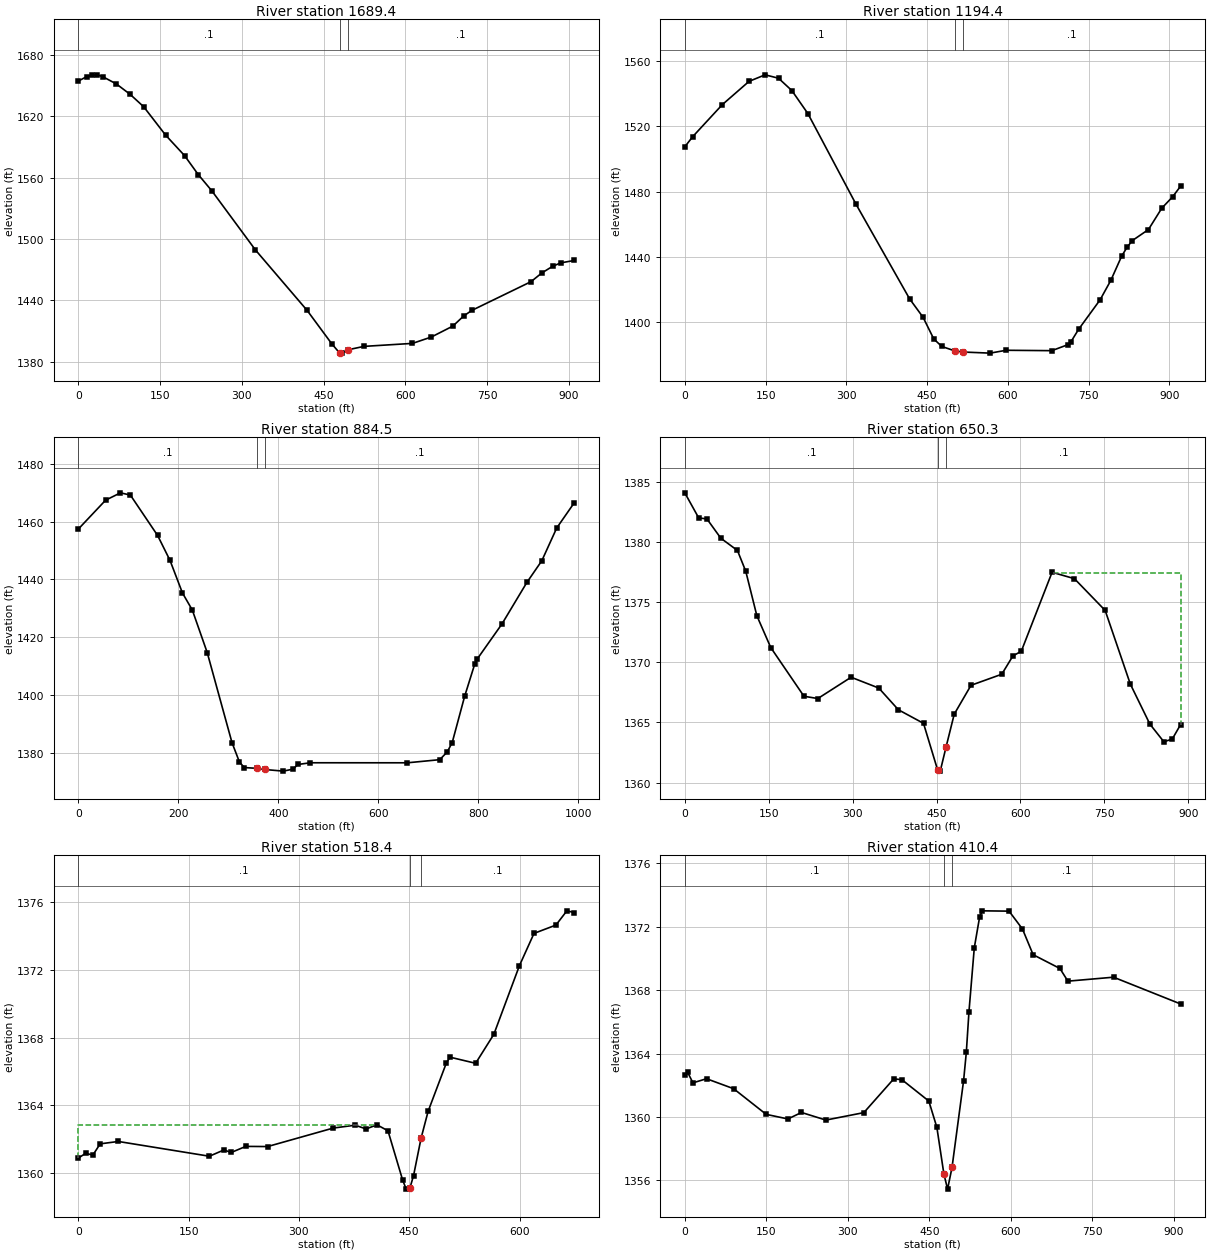
Type RM Length L Ch R = 1 ,1689.4  ,499.4,495,491.4
XS GIS Cut Line= 3
     1802952.693      244650.229     1802570.994      244897.878
     1802189.294      245145.528
#Sta/Elev= 30
       0 1654.45      15 1658.71      25 1660.13      35 1660.56      45 1658.71
      70 1651.58      95 1641.51     120 1629.33     160 1601.74     195 1581.58
     220 1563.11     245 1547.19     325 1489.42     420 1430.24   464.9 1397.84
   479.5 1388.68   479.7 1388.55   484.7  1388.7   494.5 1391.77   524.2 1395.14
   613.3 1398.07   647.9 1404.29   687.4 1414.99   707.2 1424.83   722.1 1430.28
   830.9 1458.41   850.6 1466.88   870.4 1473.39   885.3 1476.75     910 1479.11
#Mann= 3 , 0 , 0
       0      .1       0   479.5    .045       0   494.5      .1       0
Bank Sta=479.5,494.5
XS Rating Curve= 0 ,0
Exp/Cntr=0.3,0.1

Type RM Length L Ch R = 1 ,1194.4  ,305.1,309.8,313.7
XS GIS Cut Line= 3
     1802708.103      244282.417     1802288.053      244487.068
     1801951.518      244790.939
#Sta/Elev= 30
       0  1507.5    14.9  1513.8    69.6 1533.36   119.3 1547.66   149.1 1551.67
     174 1549.59   198.8 1542.01   228.6 1527.86   318.1 1472.15   417.5 1414.15
   442.4  1402.9   462.3 1389.58   477.2 1384.96   502.1 1382.17   517.1 1381.54
   566.9 1380.87   596.8 1382.62   681.5 1382.38   711.4 1386.06   716.4 1387.51
   731.3 1395.49   771.2  1413.6   791.1 1425.54   811.1 1440.31     821 1445.72
     831 1449.94   860.9  1456.7   885.8 1469.86   905.7 1476.76   920.7 1483.35
#Mann= 3 , 0 , 0
       0      .1       0   502.1    .045       0   517.1      .1       0
Bank Sta=502.1,517.1
XS Rating Curve= 0 ,0
Exp/Cntr=0.3,0.1

Type RM Length L Ch R = 1 ,884.5   ,229.8,234.2,238.7
XS GIS Cut Line= 4
     1802576.473       244164.17     1802265.902      244196.977
     1802163.107       244262.59     1801789.109      244675.956
#Sta/Elev= 30
       0 1457.41    54.5 1467.39    84.3 1469.94   104.1 1469.16   158.6 1455.19
   183.4 1446.57   208.2 1435.34     228 1429.41   257.8 1414.71   307.3 1383.62
   322.1 1376.94   331.8 1374.98   357.4  1374.7   372.4 1374.31   409.9 1373.74
   429.4 1374.43   439.2 1376.04   464.1 1376.63   658.2 1376.62   722.9  1377.7
   737.9  1380.4   747.8 1383.62   772.7 1399.63   792.6 1410.62   797.6 1412.44
   847.4 1424.64   897.1 1438.96     927 1446.46   956.8 1457.78   991.7 1466.46
#Mann= 3 , 0 , 0
       0      .1       0   357.4    .045       0   372.4      .1       0
Bank Sta=357.4,372.4
XS Rating Curve= 0 ,0
Exp/Cntr=0.3,0.1

Type RM Length L Ch R = 1 ,650.3   ,137.2,131.9,126.5
XS GIS Cut Line= 3
      1802563.35      244022.985     1802209.037       243981.43
     1801715.786      244174.081
#Sta/Elev= 30
       0 1384.08    24.8    1382    39.6 1381.91    64.4 1380.31    94.1 1379.29
     109 1377.56   128.8 1373.87   153.6 1371.23     213 1367.18   237.8 1366.99
   297.3 1368.76   346.8 1367.86   381.7 1366.06   426.7 1364.93   452.1 1361.03
   456.6 1360.96   467.1 1362.98   481.6 1365.69   511.6 1368.09   566.6 1369.01
   586.5 1370.53   601.5 1370.92   656.5 1377.48   696.4 1376.95   751.4 1374.31
   796.4 1368.19   831.3 1364.87   856.3  1363.4   871.3 1363.62   886.3 1364.83
#Mann= 3 , 0 , 0
       0      .1       0   452.1    .045       0   467.1      .1       0
#XS Ineff= 2 , 0
                          658.99         1377.38
Permanent Ineff=
       F       F
Bank Sta=452.1,467.1
XS Rating Curve= 0 ,0
Exp/Cntr=0.3,0.1

Type RM Length L Ch R = 1 ,518.4   ,110.3,108.1,105.9
XS GIS Cut Line= 3
     1802486.902      243688.307      1802215.79      243796.741
      1801902.11      244015.367
#Sta/Elev= 30
       0 1360.89     9.9 1361.17    19.8 1361.07    29.7 1361.73    54.4 1361.87
   178.2    1361     198 1361.37   207.9 1361.22   227.7 1361.58   257.4 1361.57
   346.6 1362.66   376.4 1362.83   391.3 1362.61   406.2 1362.85   421.1  1362.5
     441  1359.6   445.9 1359.06   451.1 1359.15   455.9 1359.86   466.1 1362.06
   475.7 1363.65   500.6 1366.51   505.5 1366.84   540.3 1366.48   565.1 1368.19
   599.9 1372.24   619.7 1374.14   649.5 1374.63   664.4 1375.47   674.3 1375.37
#Mann= 3 , 0 , 0
       0      .1       0   451.1    .045       0   466.1      .1       0
#XS Ineff= 2 , 0
          406.11 1362.87
Permanent Ineff=
       F       F
Bank Sta=451.1,466.1
XS Rating Curve= 0 ,0
Exp/Cntr=0.3,0.1

Type RM Length L Ch R = 1 ,410.4   ,111.5,102.9,94.2
XS GIS Cut Line= 4
     1802472.675      243633.174     1802064.307      243766.312
     1801854.377      243945.074     1801788.763      244141.915
#Sta/Elev= 30
       0 1362.62       5 1362.83      15 1362.15      40 1362.41    89.9 1361.78
   149.8 1360.16   189.8 1359.87   214.8 1360.28   259.7  1359.8   329.6 1360.27
   384.6  1362.4   399.6 1362.35   449.2    1361     464 1359.34   476.9  1356.4
   483.7 1355.44   491.9 1356.81   513.2 1362.29   518.2 1364.07   523.1 1366.65
   532.9 1370.68   542.8 1372.64   547.7 1373.01   596.9 1372.99   621.6 1371.86
   641.2 1370.24   690.5 1369.37   705.2 1368.57   789.2 1368.82   912.7 1367.13
#Mann= 3 , 0 , 0
       0      .1       0   476.9    .045       0   491.9      .1       0
#XS Ineff= 2 , 0
          393.27 1362.36
Permanent Ineff=
       F       F
Bank Sta=476.9,491.9
XS Rating Curve= 0 ,0
Exp/Cntr=0.3,0.1

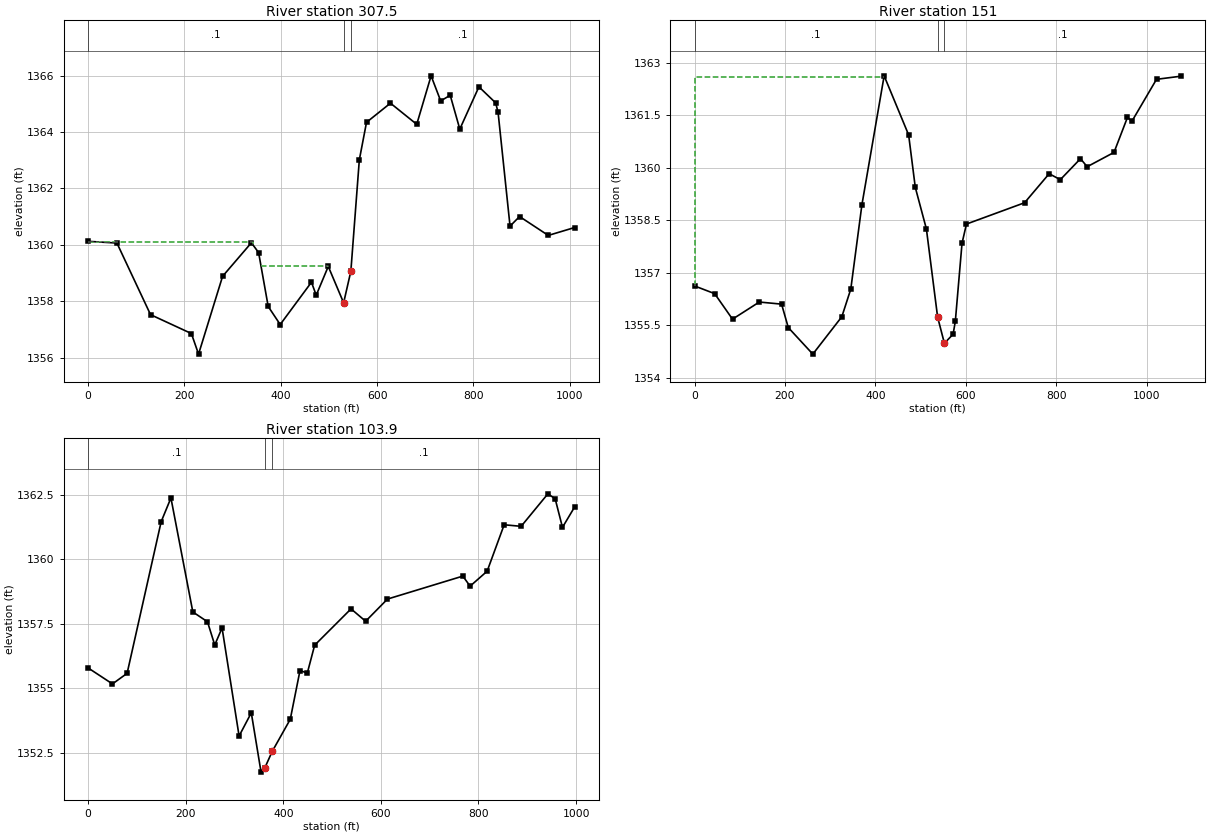
Type RM Length L Ch R = 1 ,307.5   ,142.3,156.6,170.9
XS GIS Cut Line= 3
     1802406.629       243445.18     1801975.391      243695.387
     1801689.814      244119.732
#Sta/Elev= 30
       0 1360.12    59.8 1360.06   129.6 1357.52   214.4 1356.85   229.3 1356.12
   279.2 1358.88     339 1360.07     354 1359.72   373.9 1357.81   398.8 1357.17
   463.7 1358.67   473.6 1358.21   498.6 1359.23   530.5 1357.94   545.5 1359.06
   563.1 1363.01     578 1364.34   627.7 1365.02   682.3 1364.27   712.1 1365.99
     732  1365.1   751.8  1365.3   771.7  1364.1   811.4  1365.6   846.2 1365.03
   851.2 1364.69     876 1360.66   895.8    1361   955.4 1360.33  1010.1 1360.61
#Mann= 3 , 0 , 0
       0      .1       0   530.5    .045       0   545.5      .1       0
#XS Ineff= 2 ,-1
       0  342.65 1360.08  358.69  498.66 1359.25
Permanent Ineff=
       F       F
Bank Sta=530.5,545.5
XS Rating Curve= 0 ,0
Exp/Cntr=0.3,0.1

Type RM Length L Ch R = 1 ,151     ,45.6,47,48.4
XS GIS Cut Line= 4
     1802378.936      243350.467     1802045.864      243512.152
     1801820.099      243621.746     1801634.194      244037.299
#Sta/Elev= 30
       0 1356.62    44.4  1356.4    83.9 1355.67   143.2 1356.16   192.5  1356.1
   207.3 1355.43   261.6 1354.67   325.8 1355.74   345.6 1356.53   370.2 1358.94
   419.4 1362.63   473.6 1360.94   488.3 1359.44   512.9 1358.25   537.7 1355.73
   552.7 1354.98     572 1355.24   576.9 1355.61   591.7 1357.84   601.5 1358.39
   730.1    1359   784.5 1359.83   809.2 1359.66   853.8 1360.26   868.6 1360.03
     928 1360.44   957.7 1361.44   967.6 1361.33    1022 1362.53  1076.4 1362.62
#Mann= 3 , 0 , 0
       0      .1       0   537.7    .045       0   552.7      .1       0
#XS Ineff= 2 , 0
          419.93 1362.59
Permanent Ineff=
       F       F
Bank Sta=537.7,552.7
XS Rating Curve= 0 ,0
Exp/Cntr=0.3,0.1

Type RM Length L Ch R = 1 ,103.9   ,107.7,103.9,100.2
XS GIS Cut Line= 3
     1802211.792       243405.16     1801796.239      243575.755
     1801546.907      244063.483
#Sta/Elev= 30
       0 1355.79    49.9 1355.17    79.9 1355.58   149.7 1361.46   169.7 1362.38
   214.6 1357.96   244.6 1357.58   259.5 1356.68   274.5 1357.34   309.4 1353.15
   334.4 1354.05   354.4 1351.75   362.2 1351.92   377.2 1352.55   414.3  1353.8
   434.2 1355.69   449.2 1355.59   464.2 1356.67   538.8 1358.08   568.7  1357.6
   613.5 1358.46   767.9 1359.35   782.8 1358.96   817.7 1359.54   852.6 1361.34
   887.4 1361.28   942.2 1362.54   957.1 1362.35   972.1 1361.24     997 1362.03
#Mann= 3 , 0 , 0
       0      .1       0   362.2    .045       0   377.2      .1       0
Bank Sta=362.2,377.2
XS Rating Curve= 0 ,0
Exp/Cntr=0.3,0.1

Chan Stop Cuts=-1
Use User Specified Reach Order=0